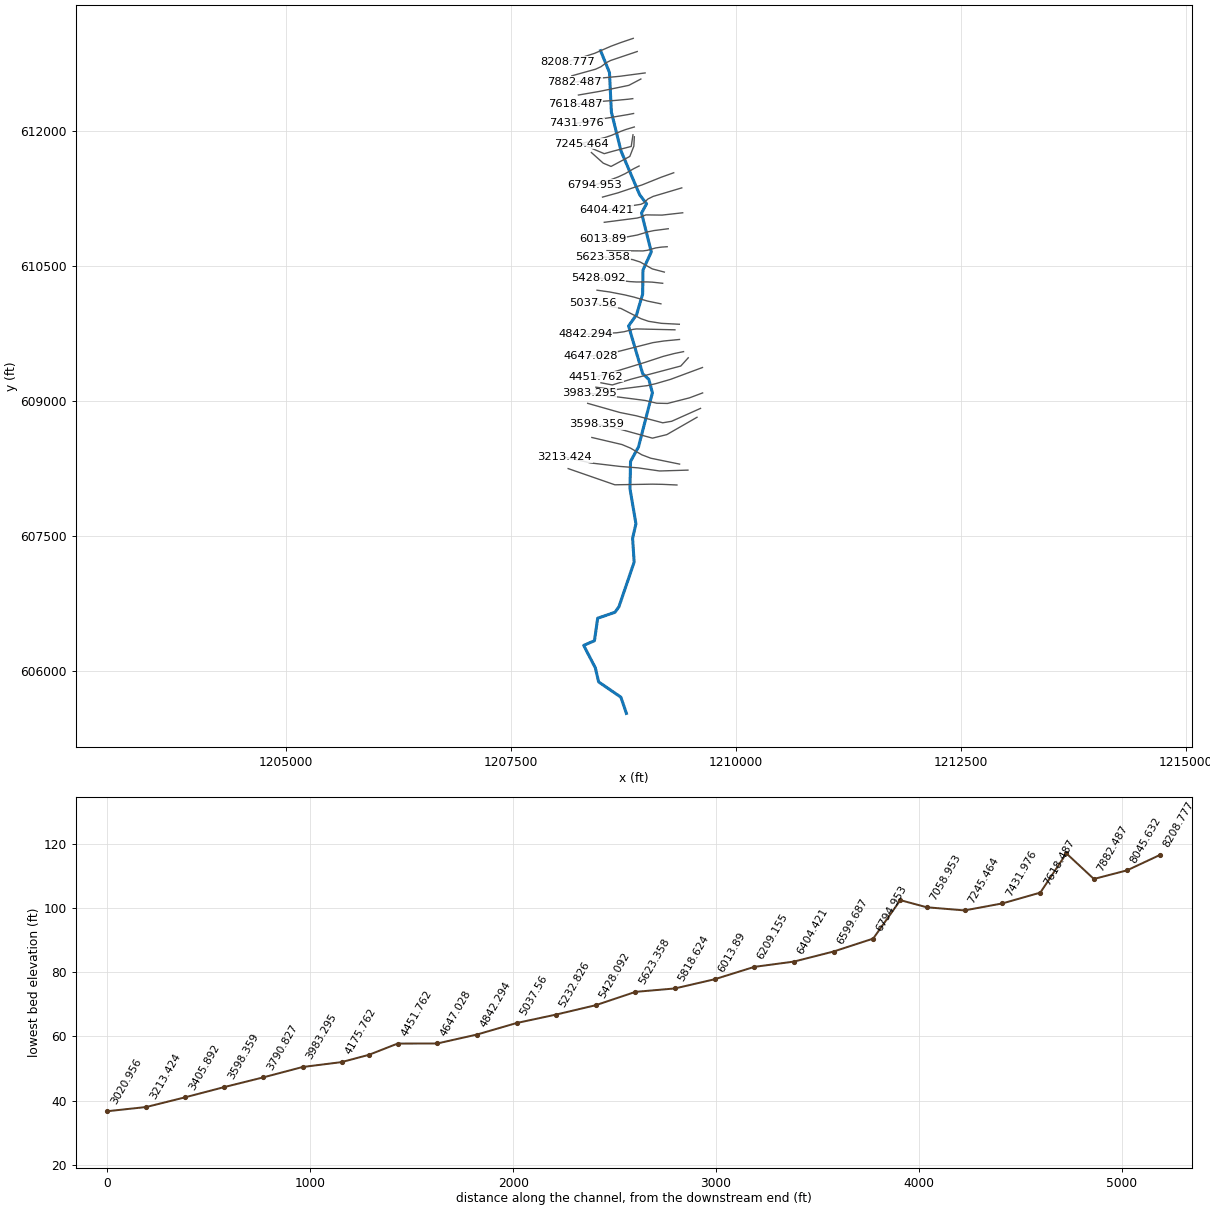
--- 60_ras.prj (project) ---

Proj Title=60
Current Plan=p01
Default Exp/Contr=0.3,0.1
English Units
Geom File=g01
Flow File=f01
Plan File=p01
Y Axis Title=Elevation
X Axis Title(PF)=Main Channel Distance
X Axis Title(XS)=Station
BEGIN DESCRIPTION:
RFD model 60 exported to HEC-RAS
END DESCRIPTION:

--- 60_ras.p01 (plan) ---

Plan Title=Plan 01
Program Version=4.10
Short Identifier=Plan 01
Geom File=g01
Flow File=f01
Subcritical Flow
Calc Critical at every XS
Secant Critical Depth

--- 60_ras.f01 (steady flow) ---

Flow Title=Flow 01
Program Version=5.01
Number of Profiles= 5
Profile Names=10yr,25yr,50yr,100yr,500yr
River Rch & RM=60,44,8208.777
  664.44   858.8 1042.65 1206.15 1569.53
River Rch & RM=60,44,8045.632
  667.11  862.75 1047.58 1212.56 1579.07
River Rch & RM=60,44,7882.487
  674.25  873.34 1060.82 1229.82 1604.79
River Rch & RM=60,44,7747.086
  677.59  878.31 1067.02 1237.92 1616.87
River Rch & RM=60,44,7618.487
   679.8   881.6 1071.14  1243.3 1624.89
River Rch & RM=60,44,7431.976
  693.94  902.63 1097.45 1277.72 1676.41
River Rch & RM=60,44,7245.464
  695.72  905.29 1100.77 1282.07 1682.94
River Rch & RM=60,44,7058.953
  703.82  917.38  1115.9 1301.92 1712.75
River Rch & RM=60,44,6928.875
  706.95  922.06 1121.75 1309.61 1724.32
River Rch & RM=60,44,6794.953
  709.02  925.16 1125.64 1314.72 1732.01
River Rch & RM=60,44,6599.687
   710.4  927.22 1128.22 1318.11 1737.12
River Rch & RM=60,44,6404.421
  743.94  977.56 1191.29 1401.32 1863.02
River Rch & RM=60,44,6209.155
  745.54  979.97 1194.31 1405.33  1869.1
River Rch & RM=60,44, 6013.89
  806.81 1072.83 1310.92 1560.66 2107.04
River Rch & RM=60,44,5818.624
  813.01 1082.28 1322.79 1576.58 2131.62
River Rch & RM=60,44,5623.358
  819.13 1091.62 1334.55 1592.35 2156.01
River Rch & RM=60,44,5428.092
  823.26 1097.94 1342.49 1603.03 2172.54
River Rch & RM=60,44,5232.826
     829 1106.71 1353.53 1617.86 2195.54
River Rch & RM=60,44, 5037.56
  832.79 1112.51 1360.83 1627.69 2210.78
River Rch & RM=60,44,4842.294
  835.21 1116.21 1365.49 1633.97 2220.54
River Rch & RM=60,44,4647.028
  839.22 1122.36 1373.23  1644.4 2236.74
River Rch & RM=60,44,4451.762
  841.88 1126.44 1378.37 1651.32  2247.5
River Rch & RM=60,44,4310.684
  842.94 1128.07 1380.41 1654.08  2251.8
River Rch & RM=60,44,3983.295
  850.56 1139.77 1395.15 1673.97 2282.77
River Rch & RM=60,44,3790.827
  852.91 1143.37 1399.69  1680.1 2292.32
River Rch & RM=60,44,3405.892
  853.95 1144.97  1401.7 1682.81 2296.56
River Rch & RM=60,44,3213.424
  866.52 1164.31 1426.08 1715.78 2348.06
River Rch & RM=60,44,2828.489
  867.79 1166.27 1428.54 1719.12 2353.27
River Rch & RM=60,44,2636.021
  869.56 1168.99 1431.97 1723.77 2360.55
River Rch & RM=60,44,2443.553
  873.33 1174.81  1439.3 1733.71 2376.11
River Rch & RM=60,44,2266.952
  875.34  1177.9  1443.2 1738.98 2384.38
River Rch & RM=60,44,2040.257
  882.29 1188.63 1456.73 1757.35 2413.18
River Rch & RM=60,44,1586.866
  887.94 1197.36 1467.74  1772.3 2436.66
River Rch & RM=60,44,453.3904
  891.35 1202.63 1474.39 1781.34 2450.88
River Rch & RM=60,44,226.6952
  913.06 1236.26 1516.83 1839.15    2542
River Rch & RM=60,44,       0
   913.3 1236.63 1517.29 1839.78 2542.99
Boundary for River Rch & Prof#=60,44,1
Up Type= 0
Dn Type= 2
Boundary for River Rch & Prof#=60,44,2
Up Type= 0
Dn Type= 2
Boundary for River Rch & Prof#=60,44,2
Up Type= 0
Dn Type= 2
Boundary for River Rch & Prof#=60,44,2
Up Type= 0
Dn Type= 2
Boundary for River Rch & Prof#=60,44,2
Up Type= 0
Dn Type= 2

--- 60_ras.g01 (geometry) ---

Geom Title=60
Program Version=4.10

River Reach=60,44
Reach XY= 30
1208494.72926664612897.5984385461208593.42803651612655.497177392
1208615.09468406 612215.497307421208721.76130676611782.997432724
1208929.26123145611296.3309046031209005.92787257611196.330932081
1208950.09455273611092.9976310431209058.42784163610661.331089437
1208965.92786315 610459.664485321208962.59452301610192.997897923
1208895.09453636609963.8313012571208805.92789236609837.998007894
1208962.59449741 609307.164827631209030.92780876 609244.66484423
 1209070.8853212609094.5109936591208916.38725278608493.952605203
1208827.84558606608332.4942718741208821.56052998608027.305970594
1208887.91669986607639.7859385611208850.75724477607477.876884058
1208867.78334469607212.6755186171208698.30075425606715.974065527
1208653.98381594606654.9432298241208462.50108162606589.535761148
1208426.47957712606339.281098425 1208307.0398517606287.144710332
1208436.90685475 606036.890047611208472.92835921605881.428817719
1208720.33921897605711.7485729161208781.95495033605531.641050518

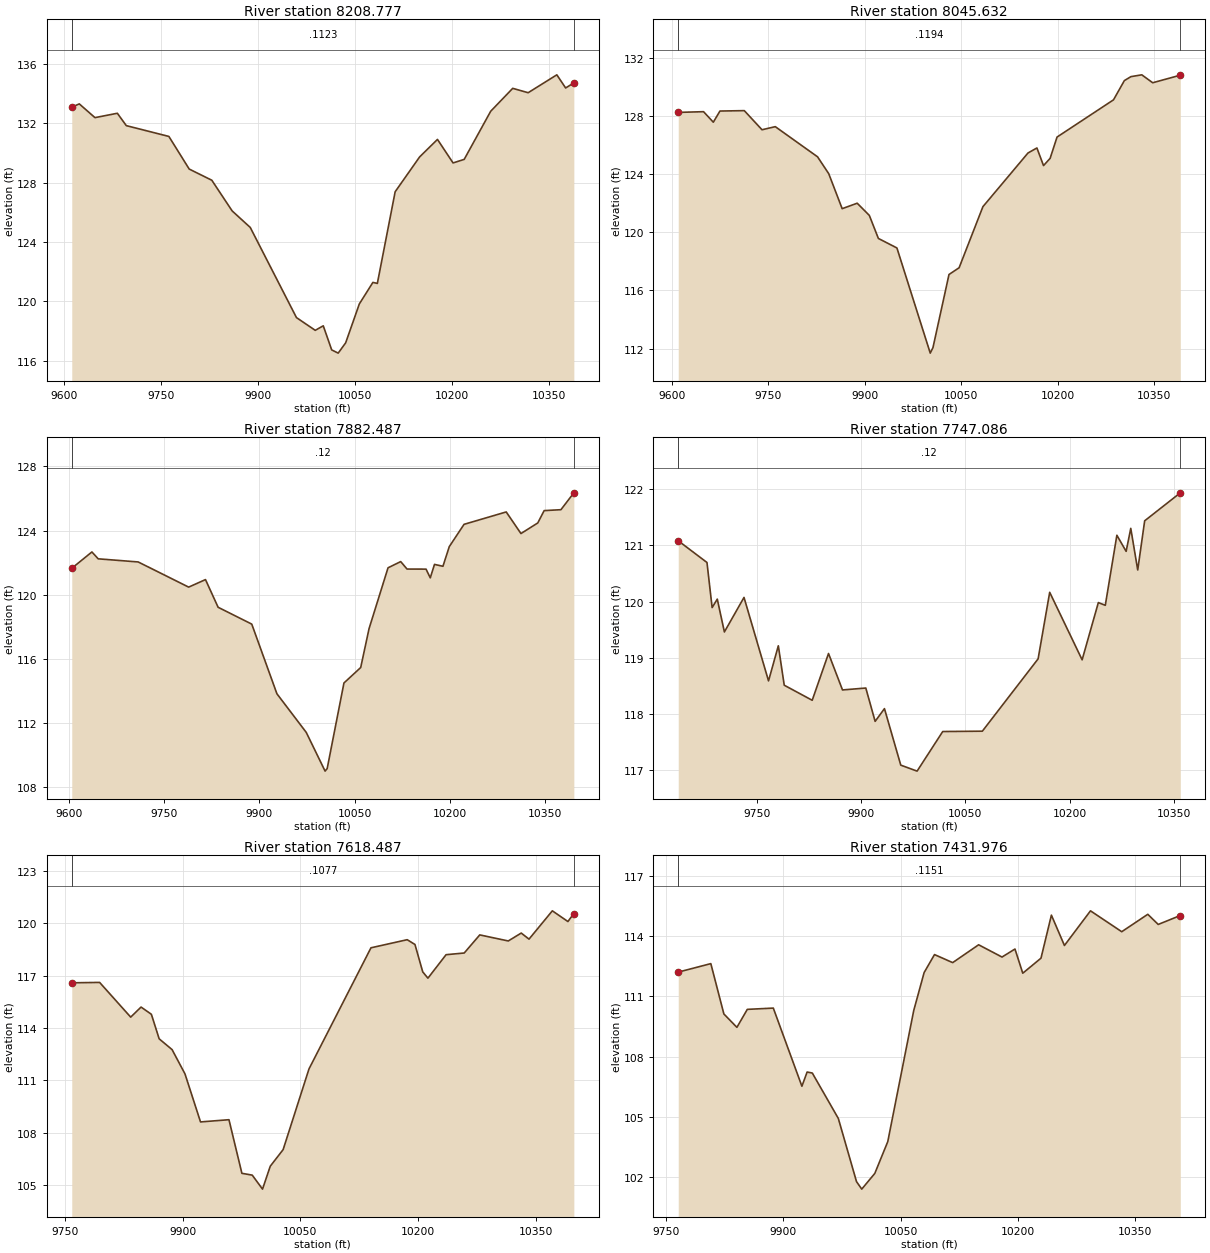
Type RM Length L Ch R = 1 ,8208.777,163.145000,163.145000,163.145000
XS GIS Cut Line= 6
1208857.96093741613035.0353293251208721.17819056612988.586647574
 1208611.3837933612947.9407131191208428.21241002612868.320238029
1208283.04065702612821.5963423031208126.05929901612776.697392346
#Sta/Elev= 30
9611.427133.07789623.082 133.2979647.335132.37269681.984132.66589695.843131.8332
9761.731131.10659793.217128.90929828.202 128.1579859.687126.09099887.696124.9792
9959.211118.90999988.308118.0521 10000.7118.356610013.75116.734110023.81 116.517
10035.39117.210810056.51119.826510077.53121.279210084.42121.209510111.99127.3821
 10149.9129.729510177.48130.9051 10201.6129.322510218.84129.561110259.85132.8009
10293.97134.344910317.86134.049910362.22135.254310375.87134.369810388.56134.7091
#Mann= 3 , 0 , 0
9611.427  0.1123       09611.427  0.1123       010388.56  0.1123       0
#XS Ineff= 2 , 0
       0                               0
Bank Sta=9611.427,10388.56
Exp/Cntr=0.3,0.1

Type RM Length L Ch R = 1 ,8045.632,163.144900,163.144900,163.144900
XS GIS Cut Line= 6
1208902.20632321612888.5682798121208607.03059685612789.114988285
1208562.32936384612766.7425822411208499.40111334612719.662610976
1208438.95003481 612691.919146361208175.38764541612618.676606576
#Sta/Elev= 30
9609.732128.23549649.092128.28479664.269127.56289674.592128.32879712.442128.3563
9739.969127.04279760.614127.25569826.311125.18419843.706124.0235 9864.58121.6195
9887.951121.99439906.801121.15759920.889119.57279949.706118.919110001.53111.6915
10005.77112.074310030.67117.095310046.38 117.55810083.38121.755110153.48125.4465
10167.34125.791410177.63124.578810187.88125.078710198.64126.540710286.41129.0987
10303.33130.422410313.49130.692510330.41130.817710347.33130.272810390.27130.7934
#Mann= 3 , 0 , 0
9609.732  0.1194       09609.732  0.1194       010390.27  0.1194       0
#XS Ineff= 2 , 0
       0                               0
Bank Sta=9609.732,10390.27
Exp/Cntr=0.3,0.1

Type RM Length L Ch R = 1 ,7882.487,135.401400,135.401400,135.401400
XS GIS Cut Line= 6
1208989.88504845612650.4673084561208703.39029951612612.643333655
1208598.87743089612602.7125842231208518.26135576612595.243351771
1208339.01798478612566.7542703411208206.71253453612548.954064897
#Sta/Elev= 30
9605.036121.6508 9636.72122.66749646.648122.24019709.524122.04559788.948120.4776
9815.422120.94669835.278119.22239888.227118.17289927.798113.83389973.936111.4279
 10003.6109.014910006.89109.175210033.25114.504610059.61115.468410072.79117.8958
10102.63121.681310122.56 122.06810132.53121.602910162.42121.598710169.07121.0554
10175.71121.8935   10189121.775910198.97122.999910222.22124.388810288.57 125.161
10311.74123.814810338.22124.476410348.24125.243810374.64125.301110394.95126.3518
#Mann= 3 , 0 , 0
9605.036    0.12       09605.036    0.12       010394.95    0.12       0
#XS Ineff= 2 , 0
       0                               0
Bank Sta=9605.036,10394.95
Exp/Cntr=0.3,0.1

Type RM Length L Ch R = 1 ,7747.086,128.598600,128.598600,128.598600
XS GIS Cut Line= 4
1208942.53535137612582.7835596651208808.89204016 612512.49881877
 1208488.7755906612446.3590564581208248.54983491612404.838555455
#Sta/Elev= 30
9637.199121.08339678.502120.69659685.915119.89279693.329120.04289703.547 119.458
9731.741120.07379766.983118.5854 9781.08119.21129789.563118.50849829.764118.2397
9853.215119.07389873.316118.42419906.817118.45819920.218 117.8649933.618118.0908
9957.069117.0834 9980.52116.976710017.37117.682610074.32117.688810154.48118.9785
10171.13120.164810217.74118.961110241.05119.981510251.04119.932910267.68121.1819
   10281120.894910287.66121.304610297.65120.563210307.64121.439510358.86121.9383
#Mann= 3 , 0 , 0
9637.199    0.12       09637.199    0.12       010358.86    0.12       0
#XS Ineff= 2 , 0
       0                               0
Bank Sta=9637.199,10358.86
Exp/Cntr=0.3,0.1

Type RM Length L Ch R = 1 ,7618.487,186.511300,186.511300,186.511300
XS GIS Cut Line= 6
1208852.63069132612364.5902823741208799.05053489612357.992918766
1208630.76089732612342.3984718981208583.94550692612340.541236291
1208444.30991903612329.1913168651208216.03753204612302.687162402
#Sta/Elev= 30
9758.823116.59249794.322116.61529833.921114.6244  9847.1 115.202 9860.28114.7863
9870.164 113.3829886.639112.76239903.113111.36719922.883108.61499959.126108.7426
9975.601 105.6689988.757105.564810001.89104.761810011.74 106.07510028.16107.0291
10061.07111.652210140.07118.599610186.22119.064810196.12118.790910206.03  117.22
10212.64 116.85810235.76118.204210258.88118.3012 10278.7119.339410315.03118.9924
10331.54119.445410341.45119.097110371.18120.720310390.99 120.10610398.57120.5665
#Mann= 3 , 0 , 0
9758.823  0.1077       09758.823  0.1077       010398.57  0.1077       0
#XS Ineff= 2 , 0
       0                               0
Bank Sta=9758.823,10398.57
Exp/Cntr=0.3,0.1

Type RM Length L Ch R = 1 ,7431.976,186.511400,186.511400,186.511400
XS GIS Cut Line= 6
 1208861.6268878612199.6600137651208798.18038149612187.451738047
1208631.57398298612159.4313747611208616.97388985612156.426456868
1208420.50063863 612125.463956271208228.55294573612091.064775219
#Sta/Elev= 30
9765.443112.20229807.143112.62499823.848110.12039840.509109.45499853.816110.3493
9887.085110.41299923.681106.52479930.335107.23169936.989107.18189970.258104.9236
9993.547101.779610000.22101.406610016.93102.187110033.54103.770410066.75110.2931
10080.04112.179810093.32113.075310116.57 112.67510149.79113.562710179.68112.9525
10196.28113.351210206.25112.147810229.56112.896110242.89115.037510259.56113.5275
10292.89115.251810332.88114.212510366.21115.079210379.55114.574310407.81115.0189
#Mann= 3 , 0 , 0
9765.443  0.1151       09765.443  0.1151       010407.81  0.1151       0
#XS Ineff= 2 , 0
       0                               0
Bank Sta=9765.443,10407.81
Exp/Cntr=0.3,0.1

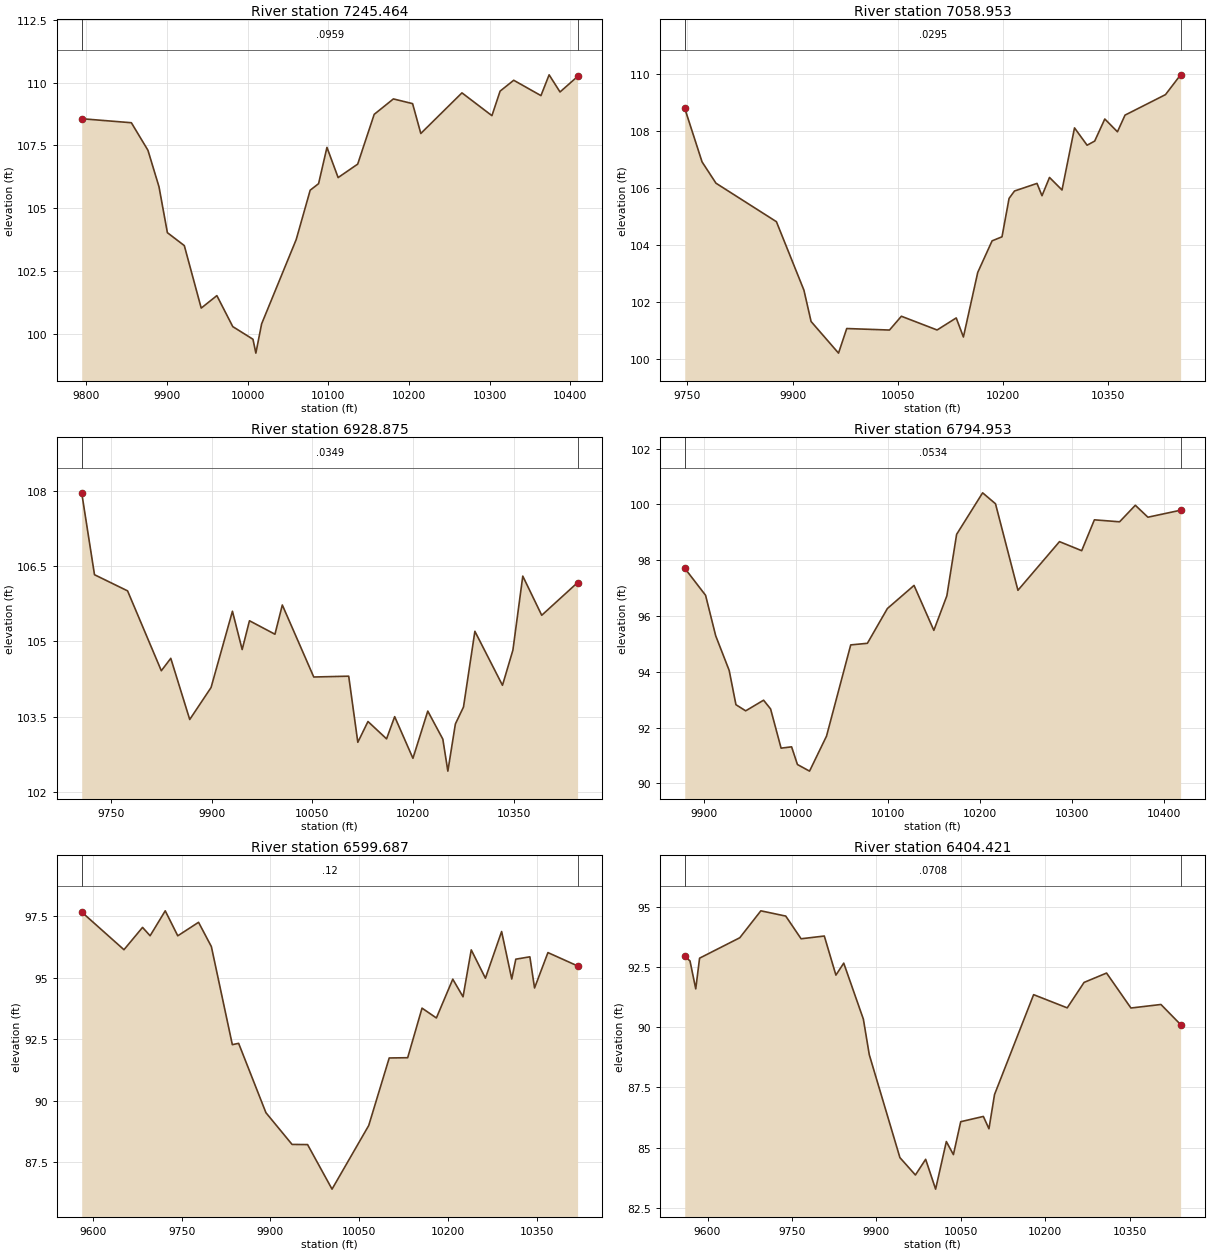
Type RM Length L Ch R = 1 ,7245.464,186.511300,186.511300,186.511300
XS GIS Cut Line= 6
 1208869.7982061612049.8525115491208774.35810891612021.267896319
 1208717.5443586612000.4039439021208620.40296468611958.227086828
1208545.76340659611932.9897925451208284.42998733611865.919840176
#Sta/Elev= 30
9794.271108.56239855.821108.4024 9876.37107.30559890.069105.85179900.476104.0213
9921.446103.50649942.417101.01579961.823101.51229981.509100.278410006.5799.77413
10010.1599.2210810017.29100.386810060.17103.748510077.49 105.71410087.88105.9737
10098.27107.420110112.12 106.21710136.37106.753210156.82108.735710180.62109.3511
10204.42109.163710214.62107.974710265.62 109.59310302.76108.683910312.89 109.662
10329.77110.094910363.54109.483510373.67110.311610387.17109.628710408.95110.2455
#Mann= 3 , 0 , 0
9794.271  0.0959       09794.271  0.0959       010408.95  0.0959       0
#XS Ineff= 2 , 0
       0                               0
Bank Sta=9794.271,10408.95
Exp/Cntr=0.3,0.1

Type RM Length L Ch R = 1 ,7058.953,130.078200,130.078200,130.078200
XS GIS Cut Line= 6
1208854.94539347611962.8388329151208835.38580364611833.659731179
1208631.50510314611780.2036937771208535.30839494611753.072929367
 1208422.9958801611800.7342100441208292.52142754611860.040779397
#Sta/Elev= 30
9746.408108.80879771.078106.92499790.938106.17449877.071104.82099916.311102.4109
9926.474101.31129965.587100.1989 9977.29 101.06410038.24101.010610055.17101.4961
10106.07101.012610133.34101.435910143.57100.766610164.02103.038510184.47104.1477
10198.58104.289410208.67105.6411 10216.4105.899810248.47106.1672 10255.6105.7337
10266.29106.376710284.11105.935710301.93108.119410319.87107.510310330.68107.6557
10345.09108.432210363.11107.982210373.92108.568410431.59109.289210453.15109.9855
#Mann= 3 , 0 , 0
9746.408  0.0295       09746.408  0.0295       010453.15  0.0295       0
#XS Ineff= 2 , 0
       0                               0
Bank Sta=9746.408,10453.15
Exp/Cntr=0.3,0.1

Type RM Length L Ch R = 1 ,6928.875,133.921800,133.921800,133.921800
XS GIS Cut Line= 6
1208869.94628054611941.0012163221208864.73794717611836.834549665
 1208819.5990583611722.2512163221208611.26572499611611.140105218
 1208524.4601694611647.5984385461208392.51572499611765.653994113
#Sta/Elev= 30
9706.527107.95839725.571106.32679774.845106.00479825.096104.41359839.201 104.661
9867.411103.44229899.147104.07839931.033105.59889945.516104.8358 9956.39105.4096
 9994.34105.141110005.32105.723610052.14104.2888 10104.2104.305210117.76102.9881
 10132.9 103.40210160.58103.056610172.65103.498710199.87102.669110221.96103.6096
10244.38103.050910251.86102.413510263.07 103.35310275.15103.690610292.12105.1995
10333.22104.123710348.73 104.82310363.46106.299110391.68105.518610445.09  106.17
#Mann= 3 , 0 , 0
9706.527  0.0349       09706.527  0.0349       010445.09  0.0349       0
#XS Ineff= 2 , 0
       0                               0
Bank Sta=9706.527,10445.09
Exp/Cntr=0.3,0.1

Type RM Length L Ch R = 1 ,6794.953,195.265900,195.265900,195.265900
XS GIS Cut Line= 6
1208922.96846468611615.8728241111208863.69350779611586.337030813
 1208768.7770876611531.0518926681208690.91008905611494.669829994
1208566.76738825611447.7842023821208428.92478806611406.010908589
#Sta/Elev= 30
9878.84897.714529901.49496.743169912.49195.290959927.15394.048089934.48492.81983
9945.07492.599949964.516 92.98129972.12492.668689983.53691.261679994.94791.30878
 10001.390.6750910014.4590.4377510032.89 91.6923 10059.294.96427 10077.395.02149
10099.0396.26872   1012897.0973910149.5195.4862410163.6596.7241510174.2598.92838
10202.52 100.418 10216.5100.025510240.8896.9232110286.0398.6676510310.1698.34352
10323.9599.4496910351.3499.3787810368.4299.9719710382.0999.5437610417.6499.79446
#Mann= 3 , 0 , 0
9878.848  0.0534       09878.848  0.0534       010417.64  0.0534       0
#XS Ineff= 2 , 0
       0                               0
Bank Sta=9878.848,10417.64
Exp/Cntr=0.3,0.1

Type RM Length L Ch R = 1 ,6599.687,195.265900,195.265900,195.265900
XS GIS Cut Line= 6
1209307.79938012611540.9372947671209167.41378279 611490.71312889
1208952.42800528611404.4057402381208872.80261884611379.701968499
1208688.34123121611317.6087731551208516.35486666611270.387115828
#Sta/Elev= 30
9581.42997.680459652.77296.149099684.13397.056439696.91996.716899722.46297.73032
9743.58796.714329778.69597.263329800.28796.278249835.72492.288869846.35592.34114
9892.42489.521179936.55888.230269962.74788.2237310004.0386.4127510065.9688.99939
10100.5791.7464610131.7391.7568310155.9693.7729810180.1993.3733810207.8994.95063
 10225.294.2337410239.0496.1417910262.9894.9901710290.3396.8886110307.4294.95668
10314.2695.7635610338.0195.8599910345.9294.5930410368.5396.0319110418.5895.48955
#Mann= 3 , 0 , 0
9581.429    0.12       09581.429    0.12       010418.58    0.12       0
#XS Ineff= 2 , 0
       0                10277.55       0
Bank Sta=9581.429,10418.58
Exp/Cntr=0.3,0.1

Type RM Length L Ch R = 1 ,6404.421,195.265900,195.265900,195.265900
XS GIS Cut Line= 6
1209397.28602702611372.8593451991209078.77890343 611277.90494594
1209021.75313373611249.5826228521208973.58491501611204.796764221
1208943.90778921611190.5123258561208563.14530898611129.870893235
#Sta/Elev= 30
9559.468 92.93729568.82492.74345 9579.0391.585999585.834 92.85879657.27393.70573
9694.69394.822519738.91794.604649766.20893.663249807.44793.777229828.06692.15583
9841.97492.653059876.87190.32833 9887.3488.855169941.78984.585569969.30483.86598
9987.50484.51647 10005.283.2793810024.2585.2525610036.81 84.711110049.79 86.0757
10090.0586.2940610099.9685.7836110109.8887.2023910179.3391.3451610239.0290.79811
10268.9691.8526910308.93 92.241710352.2390.7913610405.5390.93809 10440.590.10438
#Mann= 3 , 0 , 0
9559.468  0.0708       09559.468  0.0708       0 10440.5  0.0708       0
#XS Ineff= 2 , 0
       0                10278.36       0
Bank Sta=9559.468,10440.5
Exp/Cntr=0.3,0.1

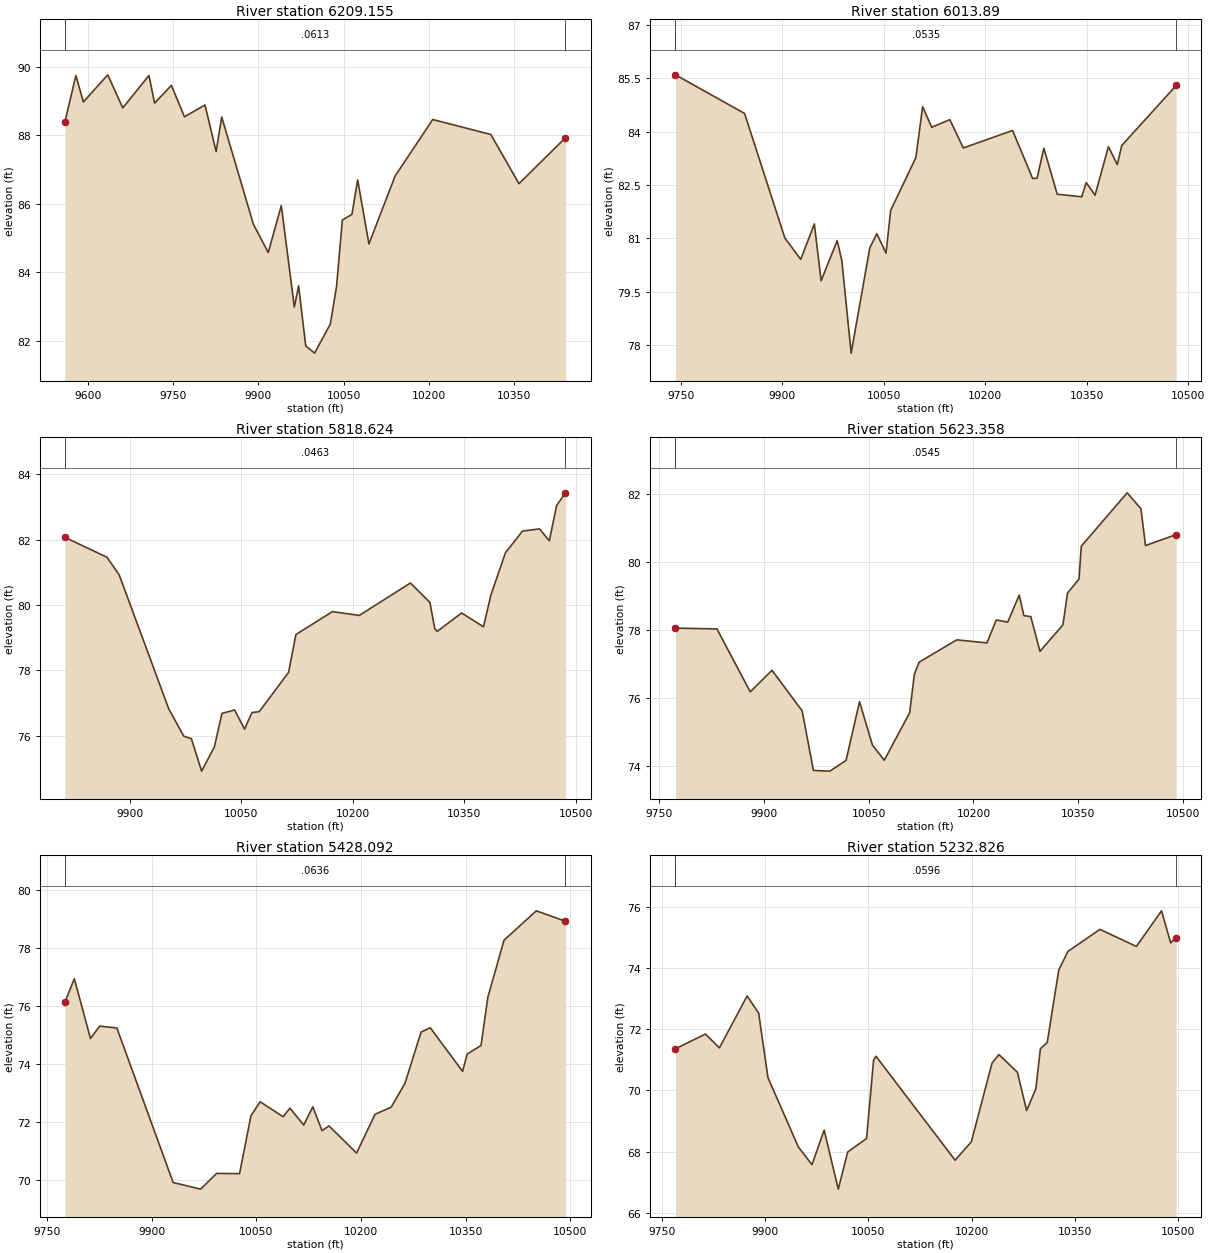
Type RM Length L Ch R = 1 ,6209.155,195.265900,195.265900,195.265900
XS GIS Cut Line= 6
1209407.59731813611095.978414354 1209177.9040749611070.223948948
1208998.10821761611072.5585062771208935.25210465611046.095715144
1208900.33317102611037.3186386041208535.91400487610990.178547799
#Sta/Elev= 30
9558.44788.370349577.94489.737089591.17788.965329634.18589.757219660.65288.79004
9706.882 89.73939716.76488.930479746.412 89.45099769.47188.531749805.64888.87705
 9825.3487.516219835.18688.524679891.00985.396929917.28884.569959940.28285.93912
9963.26582.977589970.82183.596259983.38881.84282    999981.6320110026.7482.48045
10037.7883.5843310047.9685.5183810064.87 85.6813   10075 86.689910094.85 84.8205
10141.16 86.806510207.3288.4517910309.8888.01514 10359.586.5792210441.5387.92121
#Mann= 3 , 0 , 0
9558.447  0.0613       09558.447  0.0613       010441.53  0.0613       0
#XS Ineff= 2 , 0
       0                10195.34       0
Bank Sta=9558.447,10441.53
Exp/Cntr=0.3,0.1

Type RM Length L Ch R = 1 , 6013.89,195.265900,195.265900,195.265900
XS GIS Cut Line= 6
 1209246.8599984610918.639125236 1209086.4544139610897.986988646
1209025.77397672 610885.182451271208901.57558865  610848.4862492
1208796.17371818610829.0581140041208517.37673228610804.085088165
#Sta/Elev= 30
9741.75485.592399843.94484.507879903.522 81.00989926.99480.410849947.11281.40439
9957.17179.811239980.98480.936689987.84180.3652710001.57 77.777310029.1680.73474
10039.5181.1303710053.1880.5842510059.9781.7802110097.26 83.2673 10107.384.69472
 10120.784.1206610147.4984.3335610167.4783.5381610240.3284.0299510270.0382.68085
10276.6482.6905510286.5483.5317610306.3582.24022 10342.682.1668710349.1882.56552
10362.3382.2129610382.0783.5749310395.2383.0724810401.8183.6083410482.22 85.2927
#Mann= 3 , 0 , 0
9741.754  0.0535       09741.754  0.0535       010482.22  0.0535       0
#XS Ineff= 2 , 0
       0                10151.67       0
Bank Sta=9741.754,10482.22
Exp/Cntr=0.3,0.1

Type RM Length L Ch R = 1 ,5818.624,195.265800,195.265800,195.265800
XS GIS Cut Line= 6
1209235.02694591 610718.792016451209169.29870668610714.257646018
1209106.97965728610705.0896155221209013.94451845610678.646806129
 1208964.4355534610671.9137802731208565.98278691610675.268260158
#Sta/Elev= 30
9812.19882.07319 9869.0781.461979885.57580.914039952.087  76.8279972.34675.98808
9982.64475.909859996.37474.9185910013.5175.65461 10023.8 76.685410040.8676.79045
10054.2176.2028110064.1776.7114410074.0676.73972 10113.577.9407110123.3479.09811
10172.56 79.799410208.6579.6824110277.5680.67428 10303.880.0803810310.3779.27673
10313.6579.1943410346.4679.7576410375.9979.3353510385.8380.3019910405.5281.60056
10428.4982.2642410451.4582.3303910464.5881.9654610474.4283.0465610486.3483.43409
#Mann= 3 , 0 , 0
9812.198  0.0463       09812.198  0.0463       010486.34  0.0463       0
#XS Ineff= 2 , 0
       0                10198.87       0
Bank Sta=9812.198,10486.34
Exp/Cntr=0.3,0.1

Type RM Length L Ch R = 1 ,5623.358,195.265900,195.265900,195.265900
XS GIS Cut Line= 6
1209203.44499059610436.7728664981209069.14202762 610472.45716963
1208935.69291615610548.4070878271208851.49433213610575.567755582
1208706.92691343610595.2326103611208517.64267233610604.881495494
#Sta/Elev= 30
9773.12978.044999832.55378.020929880.22676.172329911.33576.805979954.591 75.6144
9970.74273.86269 9994.4873.8424810017.5474.1594610036.7875.8824210055.3274.60637
10072.2874.1630910108.5875.5566210115.3776.6888210122.1777.0444110176.1177.69986
10219.3777.6103310232.6378.2834710249.1278.2217510265.6179.0168110272.2178.41221
 10282.178.38331 10295.377.3622410328.19 78.139710334.7679.07502 10351.2  79.486
10354.48 80.452810420.2182.02076 10439.981.5529310446.4780.4715510490.3580.79318
#Mann= 3 , 0 , 0
9773.129  0.0545       09773.129  0.0545       010490.35  0.0545       0
#XS Ineff= 2 , 0
       0                10209.82       0
Bank Sta=9773.129,10490.35
Exp/Cntr=0.3,0.1

Type RM Length L Ch R = 1 ,5428.092,195.265900,195.265900,195.265900
XS GIS Cut Line= 6
1209185.23917623610312.2450964341209067.46675691 610325.18433159
1209006.99081351610327.633257847  1208895.155451610326.774947961
1208820.64494841610330.9419127411208470.73647329610371.738728719
#Sta/Elev= 30
9775.40676.117549789.02176.934389812.16574.877459825.38975.301779849.979 75.2402
9930.74269.925449970.13369.69828  9993.170.2395910025.9170.2299510042.3172.22554
10055.4472.7032510088.2872.1875810098.1472.4821410117.8571.90343   1013172.52628
10144.1671.7067110154.0771.87345 10193.770.9375210220.13 72.270710243.2572.51589
10263.0773.3364410286.19 75.0993 10299.475.2453410345.6473.7472710352.2574.34335
10372.0774.6360310381.9876.30719 10405.178.2570410451.3479.2671310493.1778.90791
#Mann= 3 , 0 , 0
9775.406  0.0636       09775.406  0.0636       010493.17  0.0636       0
#XS Ineff= 2 , 0
       0                               0
Bank Sta=9775.406,10493.17
Exp/Cntr=0.3,0.1

Type RM Length L Ch R = 1 ,5232.826,195.265900,195.265900,195.265900
XS GIS Cut Line= 6
1209165.50171604 610083.941922791209018.03659091 610114.21013135
1208864.83998989610158.9641242361208760.98770882610183.749307221
1208596.81158348610215.4607708111208455.19646218610235.596425795
#Sta/Elev= 30
9769.79771.360969813.43471.838789833.56671.387679873.86773.084549890.65972.52016
9904.093 70.41939948.20168.157129968.04267.573999985.74868.7044810006.24 66.7771
10019.9367.9892210047.3168.4287110057.5870.9913210061.0171.1151510175.9667.72103
10199.4968.3195510229.6370.8939710239.6871.1699810266.4870.5912310279.8369.34272
10293.1770.0463610299.8471.3589310309.8471.5693210326.51 73.929810339.8474.53851
10386.3275.2555810439.3474.7005910475.79 75.862610489.0574.81609   1049774.98048
#Mann= 3 , 0 , 0
9769.797  0.0596       09769.797  0.0596       0   10497  0.0596       0
#XS Ineff= 2 , 0
       0                               0
Bank Sta=9769.797,10497
Exp/Cntr=0.3,0.1

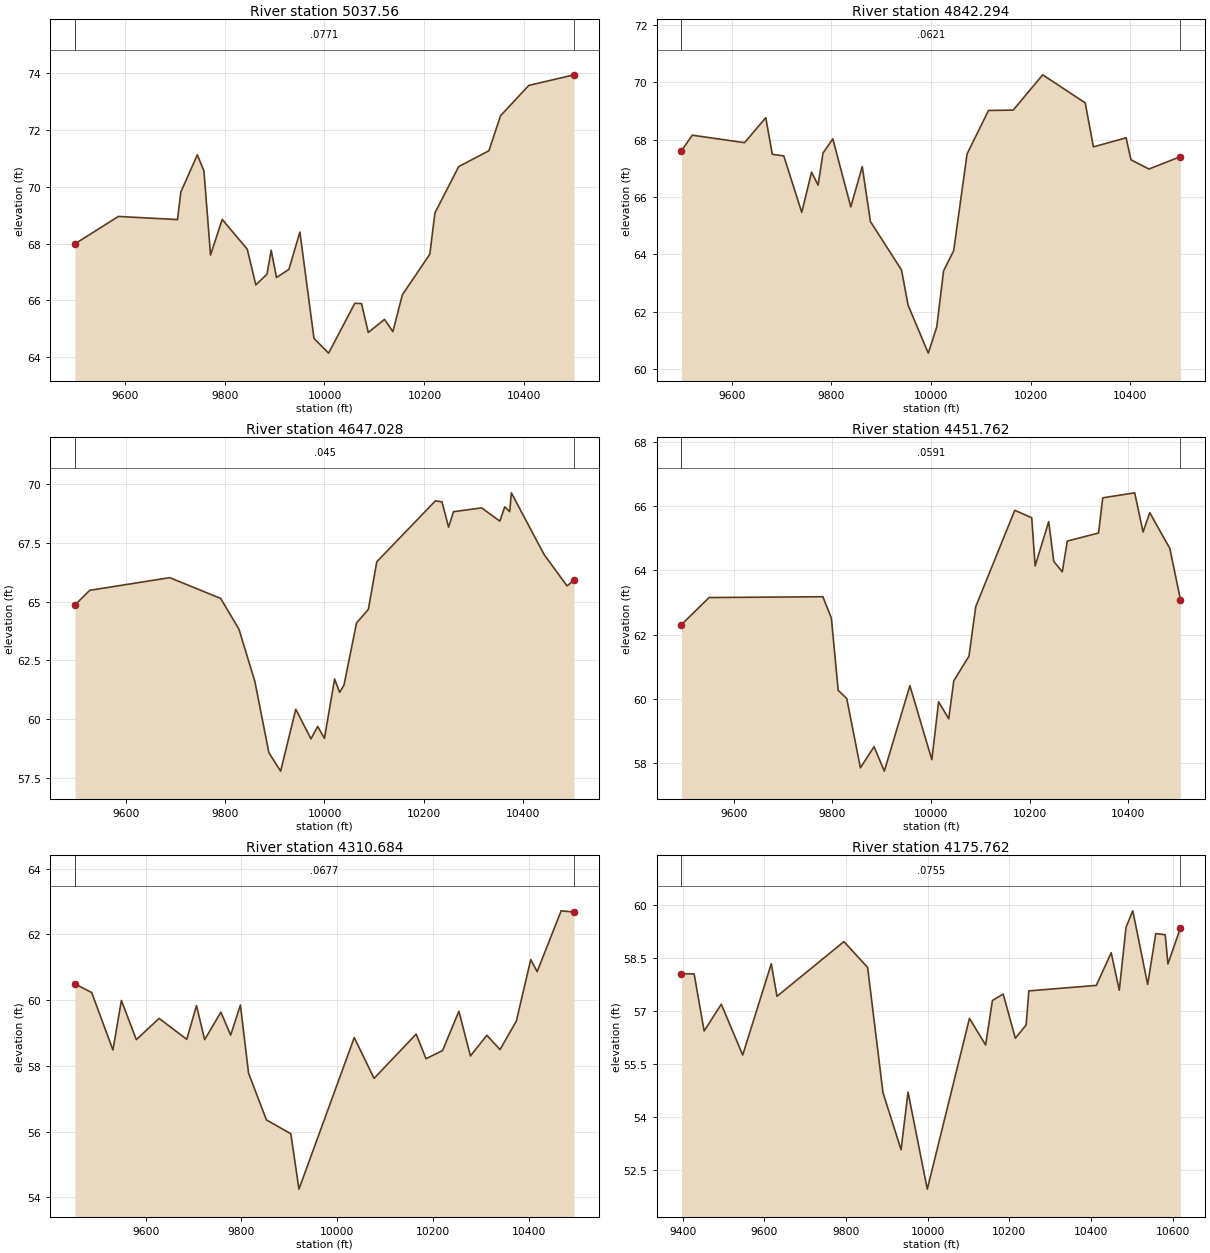
Type RM Length L Ch R = 1 , 5037.56,195.265900,195.265900,195.265900
XS GIS Cut Line= 6
1209370.06245592609856.7976019891209171.71285481609867.049296898
1209027.60386249609889.7082063621208943.97718516609918.632812152
1208720.24174509610032.6758807181208412.67506779610092.485366497
#Sta/Elev= 30
9500.53567.990079587.372 68.95589705.775 68.84599712.38569.814449745.43371.12707
9758.65270.564529771.87167.59626 9795.2568.851269845.39867.801449862.50766.54281
9884.86166.918529893.30367.761049903.91466.801649928.72567.089249950.75768.40531
9979.022 64.653410008.2764.1371410060.7465.8953910074.1765.8836610087.6564.86365
10120.16 65.328410136.9264.8940110155.8866.1941410210.8467.6234710221.0869.08035
10268.7170.7143510329.1171.2706510352.48 72.505510408.9973.5750710499.4873.94832
#Mann= 3 , 0 , 0
9500.535  0.0771       09500.535  0.0771       010499.48  0.0771       0
#XS Ineff= 2 , 0
       0                               0
Bank Sta=9500.535,10499.48
Exp/Cntr=0.3,0.1

Type RM Length L Ch R = 1 ,4842.294,195.265900,195.265900,195.265900
XS GIS Cut Line= 6
1209321.39168442609795.0979706421208893.25175083609805.079901964
1208855.35106857609799.8363918631208755.16405228609773.621193287
1208671.98823539609761.8803376681208324.40084137609745.601978205
#Sta/Elev= 30
9498.90267.611959520.61468.158529625.60267.896729668.25468.769049681.37767.49061
9704.36667.435599740.49265.462599760.19866.865539773.33466.415529783.18767.53386
9802.89268.029039839.01865.655549862.00867.061879878.42865.142579940.89963.45179
9954.14762.217969994.62660.5485610011.6761.4618410025.32 63.417410045.6464.12378
10072.5267.5028110115.5969.02135 10165.269.0337610224.3970.2656410309.8669.28516
10326.2767.7495610391.9268.0666210401.7767.2976910437.8866.9761510501.12 67.4104
#Mann= 3 , 0 , 0
9498.902  0.0621       09498.902  0.0621       010501.12  0.0621       0
#XS Ineff= 2 , 0
       0                               0
Bank Sta=9498.902,10501.12
Exp/Cntr=0.3,0.1

Type RM Length L Ch R = 1 ,4647.028,195.265900,195.265900,195.265900
XS GIS Cut Line= 6
   1209371.94383609687.7415499521209199.57122112 609671.07460528
1209076.14654384 609652.529310731208663.89095741609547.128562169
1208537.75723067 609523.042401161208383.52981064609502.621972148
#Sta/Elev= 30
9496.19964.85904 9525.9565.481859687.57966.022879790.426 65.1358 9827.3363.82364
9859.42761.596389887.796 58.55659911.41557.774689942.05460.410019972.69259.15123
9986.30959.68082 9999.9359.1707710020.3961.7009810030.6161.1325910039.3561.44003
10064.7164.0913810088.5764.6710910105.6266.6989610223.8769.2942710237.23  69.256
10250.5968.1759610260.6168.8335510317.39 68.997310354.0968.4315810364.0469.04306
10373.9968.8366510377.3169.6386310443.5567.0039710489.8165.6709810503.8365.91186
#Mann= 3 , 0 , 0
9496.199   0.045       09496.199   0.045       010503.83   0.045       0
#XS Ineff= 2 , 0
       0                               0
Bank Sta=9496.199,10503.83
Exp/Cntr=0.3,0.1

Type RM Length L Ch R = 1 ,4451.762,141.078200,141.078200,141.078200
XS GIS Cut Line= 6
1209416.87956075609552.6287883261209313.57353122609531.452373953
 1209191.0699644609499.8487639581208983.33132221 609431.54108739
1208681.88786373609339.373197087 1208445.6344601609273.295290794
#Sta/Elev= 30
9494.39762.310979550.40163.154979780.96863.180779798.175 62.51579812.02560.26245
9829.33760.009279857.03657.846859884.73558.506289905.50957.743349957.31360.40736
10001.8458.0989910015.52 59.904410036.0459.37622 10046.360.5605310077.0861.32884
10090.7862.8725410169.8665.8753210204.2465.6428110211.1164.1405510238.6265.52022
10248.9364.2835610266.09 63.957510276.3564.9160810339.6165.1672710348.1666.26431
10412.8766.4200810429.8565.1993710443.4465.8011110484.1964.6820310505.6363.08465
#Mann= 3 , 0 , 0
9494.397  0.0591       09494.397  0.0591       010505.63  0.0591       0
#XS Ineff= 2 , 0
       09714.289        10152.44       0
Bank Sta=9494.397,10505.63
Exp/Cntr=0.3,0.1

Type RM Length L Ch R = 1 ,4310.684,134.921800,134.921800,134.921800
XS GIS Cut Line= 5
1209469.12162778609483.9699663371209386.65634999609392.824133009
1208837.61121109609247.4248274271208624.93759999609182.320660785
1208499.06954443609206.192188561
#Sta/Elev= 30
9452.71460.493079487.63560.228959531.87858.483459549.57659.990149580.75558.79688
 9628.2759.444949685.96758.806859706.33159.83356  9723.358.79667 9757.2459.63316
9777.60358.935539797.96759.849699814.936  57.778 9852.2756.355599903.17855.93474
9920.14854.2494410035.5458.8596210076.8857.6194410164.7458.9654110185.33 58.2184
10219.7558.4633510253.9559.6614210277.9758.3008610312.2858.9300210339.7358.49564
10373.8259.3626610403.8861.2330810417.2360.8655610467.32 62.716910494.1362.67989
#Mann= 3 , 0 , 0
9452.714  0.0677       09452.714  0.0677       010494.13  0.0677       0
#XS Ineff= 2 , 0
       09740.916        10143.34       0
Bank Sta=9452.714,10494.13
Exp/Cntr=0.3,0.1

Type RM Length L Ch R = 1 ,4175.762,192.467700,192.467700,192.467700
XS GIS Cut Line= 6
1209627.39280361609376.2082358151209273.16982719609244.607499063
1209109.13092622609197.0275771621209019.12319446609175.362746045
1208651.13943136609128.9648630471208442.49697033 609157.45823583
#Sta/Elev= 30
9396.56158.053259427.66558.050059452.16556.437169494.16457.194859546.66355.75872
9616.66258.336349630.662 57.41759794.66258.961829852.73558.233929890.31254.69755
 9934.7253.08407 9951.7254.711899998.95251.9711810102.26 56.793610141.9456.04226
10158.4857.2991210184.9357.4808510214.6956.2336510241.1556.6060310247.7657.57071
10413.1157.7258610449.5358.64822 10469.457.5905810485.9559.3665310502.5159.83177
10538.9457.75238 10558.859.1887610581.9859.15673 10588.6 58.3325 10619.359.34945
#Mann= 3 , 0 , 0
9396.561  0.0755       09396.561  0.0755       0 10619.3  0.0755       0
#XS Ineff= 2 , 0
       09803.839        10194.47       0
Bank Sta=9396.561,10619.3
Exp/Cntr=0.3,0.1

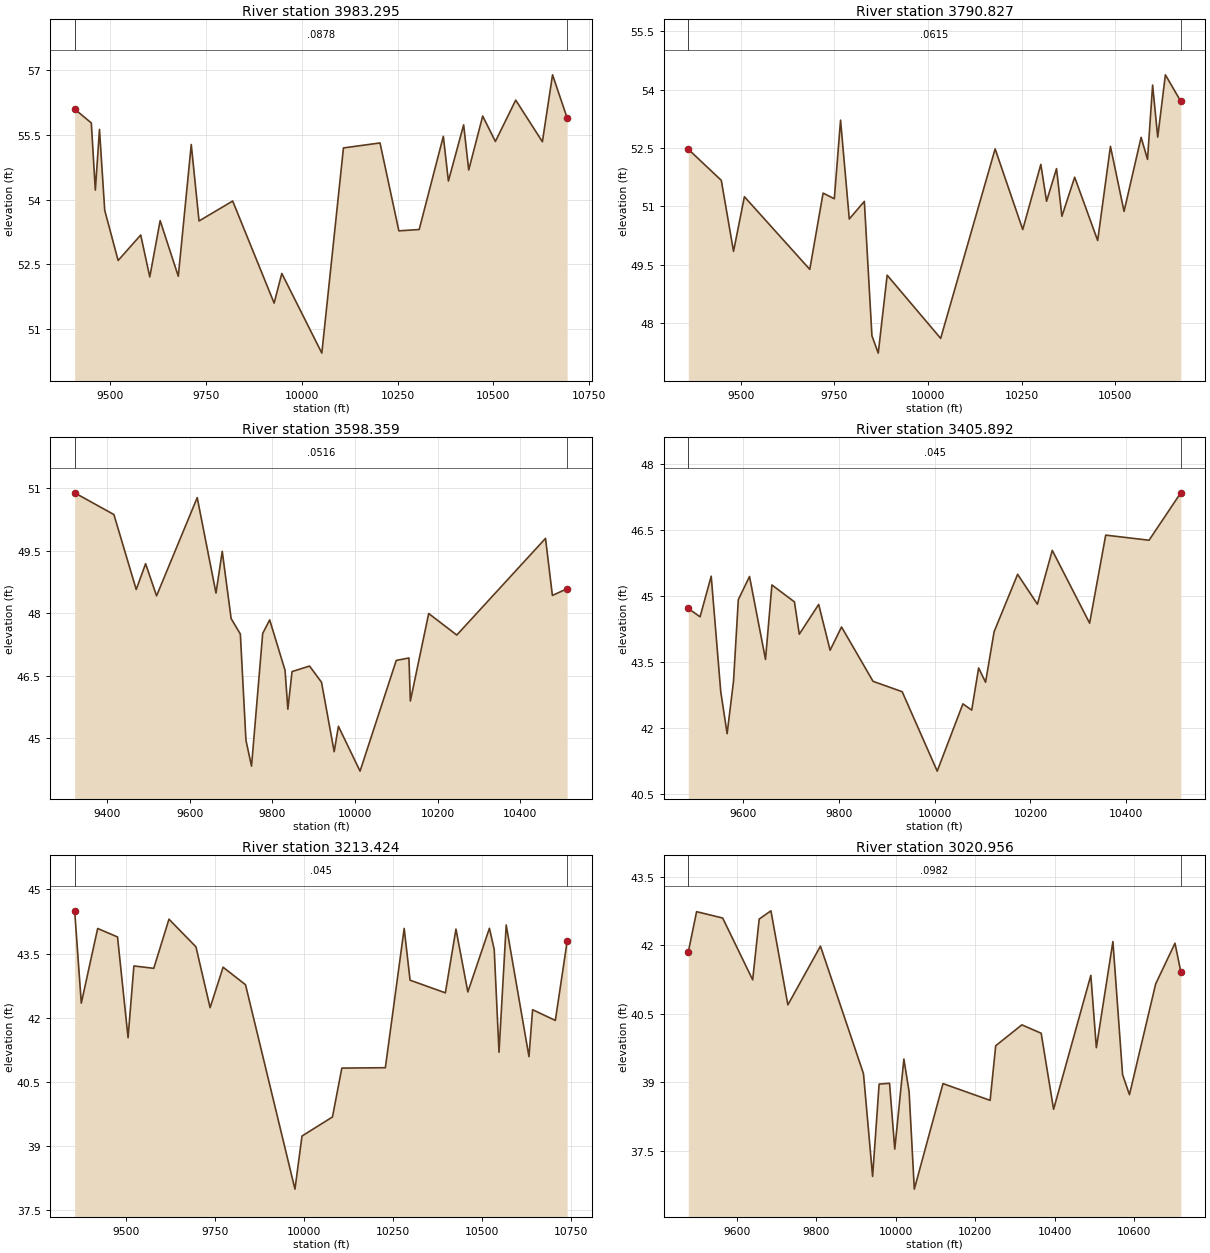
Type RM Length L Ch R = 1 ,3983.295,192.467700,192.467700,192.467700
XS GIS Cut Line= 6
1209629.11013469 609093.700494261209483.27680138 609039.01299426
1209238.48513469 608976.512994261209118.56591314608979.397676975
1208990.72066197609009.7721140381208369.58030361609089.749902487
#Sta/Elev= 30
9406.488  56.0979449.97355.776239460.48554.220199471.31955.625769485.01353.75234
9520.05252.589669579.03453.179679602.73752.209469629.82553.51307 9677.2352.22372
9711.09155.276169731.40853.504959819.30553.966919927.604 51.60199947.64952.28985
10052.1950.4432510108.6955.1970810204.19 55.312710253.46 53.276110306.5553.30692
10369.5955.4661410382.8654.4294610422.6755.7322210435.9454.6854810472.44 55.9358
10505.6255.34712 10558.756.3045210628.3855.3413610654.9256.8908310693.0655.89207
#Mann= 3 , 0 , 0
9406.488  0.0878       09406.488  0.0878       010693.06  0.0878       0
#XS Ineff= 2 , 0
       09897.844        10160.33       0
Bank Sta=9406.488,10693.06
Exp/Cntr=0.3,0.1

Type RM Length L Ch R = 1 ,3790.827,192.467700,192.467700,192.467700
XS GIS Cut Line= 6
1209605.67263466 608921.825494261209285.36013469608778.596327603
1209186.03838781608761.4571753891208891.31617114608839.571815833
1208710.70615846608875.7761698221208351.35113698 608977.77073583
#Sta/Elev= 30
9359.92952.466649447.97451.667349480.62849.842879509.65451.247289684.154 49.3799
9719.68851.339969749.65251.195029766.29853.214829789.60350.674939829.79551.12736
9850.03947.674389866.90947.228129890.66649.2309510033.4847.60762 10178.952.47519
10252.5750.4030310300.8852.0777110316.1651.1295710342.7651.9685410357.09 50.7442
10391.1951.7482710452.5850.1208210486.6852.54075   1052350.8701110568.5352.77292
10585.5952.2060710599.2354.1147310612.8752.7783310633.3354.3787410674.4353.69736
#Mann= 3 , 0 , 0
9359.929  0.0615       09359.929  0.0615       010674.43  0.0615       0
#XS Ineff= 2 , 0
       09914.051        10129.37       0
Bank Sta=9359.929,10674.43
Exp/Cntr=0.3,0.1

Type RM Length L Ch R = 1 ,3598.359,192.467700,192.467700,192.467700
XS GIS Cut Line= 6
1209566.61013469608822.8671609311209230.67263466608630.158827603
1209071.04016078608590.8739922051208659.32586652608704.713098407
1208562.16854548608725.0444043871208450.80539861 608743.16862461
#Sta/Elev= 30
9322.02350.887779416.89250.366649470.89748.565989493.59149.185049520.06748.41339
9618.40750.773079663.79548.479979678.92449.481789700.41247.866949722.71147.49542
9736.22644.945799749.74144.32321 9776.7747.510239793.664 47.8358 9830.8346.62355
9837.58745.690189847.72446.59412 9890.0646.727339918.99946.337649949.62644.66997
9959.83445.2805710012.1944.2031810099.7246.8617610130.4346.9214610133.8445.88715
10178.2147.9889810246.1347.4717810460.6849.79369 10477.348.4228310512.9948.58461
#Mann= 3 , 0 , 0
9322.023  0.0516       09322.023  0.0516       010512.99  0.0516       0
#XS Ineff= 2 , 0
       09887.307        10132.82       0
Bank Sta=9322.023,10512.99
Exp/Cntr=0.3,0.1

Type RM Length L Ch R = 1 ,3405.892,192.467600,192.467600,192.467600
XS GIS Cut Line= 6
1209373.13905136608302.3061623481209053.57553546608367.712058747
1208953.37158384  608405.6473556 1208827.6289141 608480.07285453
1208732.28889887608519.9259674191208397.79920191608598.413598988
#Sta/Elev= 30
9486.35244.715899510.87944.526319534.11245.447739554.02542.828429567.32241.87472
9580.66543.067449590.672 44.91569614.02245.441339647.37943.560599660.72245.24974
9707.75344.864799717.84744.131949758.30744.807379782.13843.76829 9805.9744.29586
9871.69443.063039932.50542.8271310005.5641.0254110059.1842.5516410077.5242.40957
10091.9643.36529 10106.443.0420410124.2444.1883910173.2945.4906310214.5744.81293
10245.5846.0340110323.4944.3822310357.0546.3795510447.4646.2639310513.6547.33937
#Mann= 3 , 0 , 0
9486.352   0.045       09486.352   0.045       010513.65   0.045       0
#XS Ineff= 2 , 0
       09823.429        10134.24       0
Bank Sta=9486.352,10513.65
Exp/Cntr=0.3,0.1

Type RM Length L Ch R = 1 ,3213.424,192.467700,192.467700,192.467700
XS GIS Cut Line= 6
 1209465.9344703608235.5832358151209150.91118598608225.970008209
1208911.99852973608260.5724508021208711.07863623608276.522063106
 1208385.3694002608315.0939036911208096.14280364608381.416569173
#Sta/Elev= 30
9355.57244.500639374.19742.33961 9420.15 44.0873 9475.95 43.88889505.49141.53172
9521.90343.210899577.70343.154529620.37444.304889696.119  43.6589735.89942.23424
9772.36543.180899835.35142.771019974.14437.987429993.89439.2297310079.4539.67635
10105.7840.8198610227.9940.8289510280.8544.0887210297.3742.8773510396.4842.58155
10426.2244.0727810459.5842.6016810520.1744.0920210533.64 43.5982 10547.141.19075
 10567.344.1691610631.25  41.08810641.3542.18636 10705.341.9355210738.42 43.7836
#Mann= 3 , 0 , 0
9355.572   0.045       09355.572   0.045       010738.42   0.045       0
#XS Ineff= 2 , 0
       09790.988        10280.22       0
Bank Sta=9355.572,10738.42
Exp/Cntr=0.3,0.1

Type RM Length L Ch R = 1 ,3020.956,192.467700,192.467700,192.467700
XS GIS Cut Line= 6
1209343.45583302608070.138075069 1209184.6925883608077.255298361
1209070.36690503608079.4803234931208822.56053001608075.277016312
1208653.28191999608072.453881323  1208134.318468608252.554660916
#Sta/Elev= 30
9477.88841.853099498.719 42.73439564.40142.595429639.93441.243559656.341 42.5731
9685.87442.752849728.53340.697159810.56641.98079 9918.8539.192619941.81936.94606
9958.22538.964429984.47638.982089997.60137.5426110020.5739.5118610033.6938.79974
10046.8236.6681410119.0138.9752710237.6838.6088210251.7439.8035110317.5540.25997
10366.1740.0763810397.4338.4129810491.1941.3422310505.0839.7603410546.7642.08155
10571.0739.1729210588.4338.7330710654.4141.1556110703.0342.0438610717.6341.42229
#Mann= 3 , 0 , 0
9477.888  0.0982       09477.888  0.0982       010717.63  0.0982       0
#XS Ineff= 2 , 0
       09813.895        10196.55       0
Bank Sta=9477.888,10717.63
Exp/Cntr=0.3,0.1