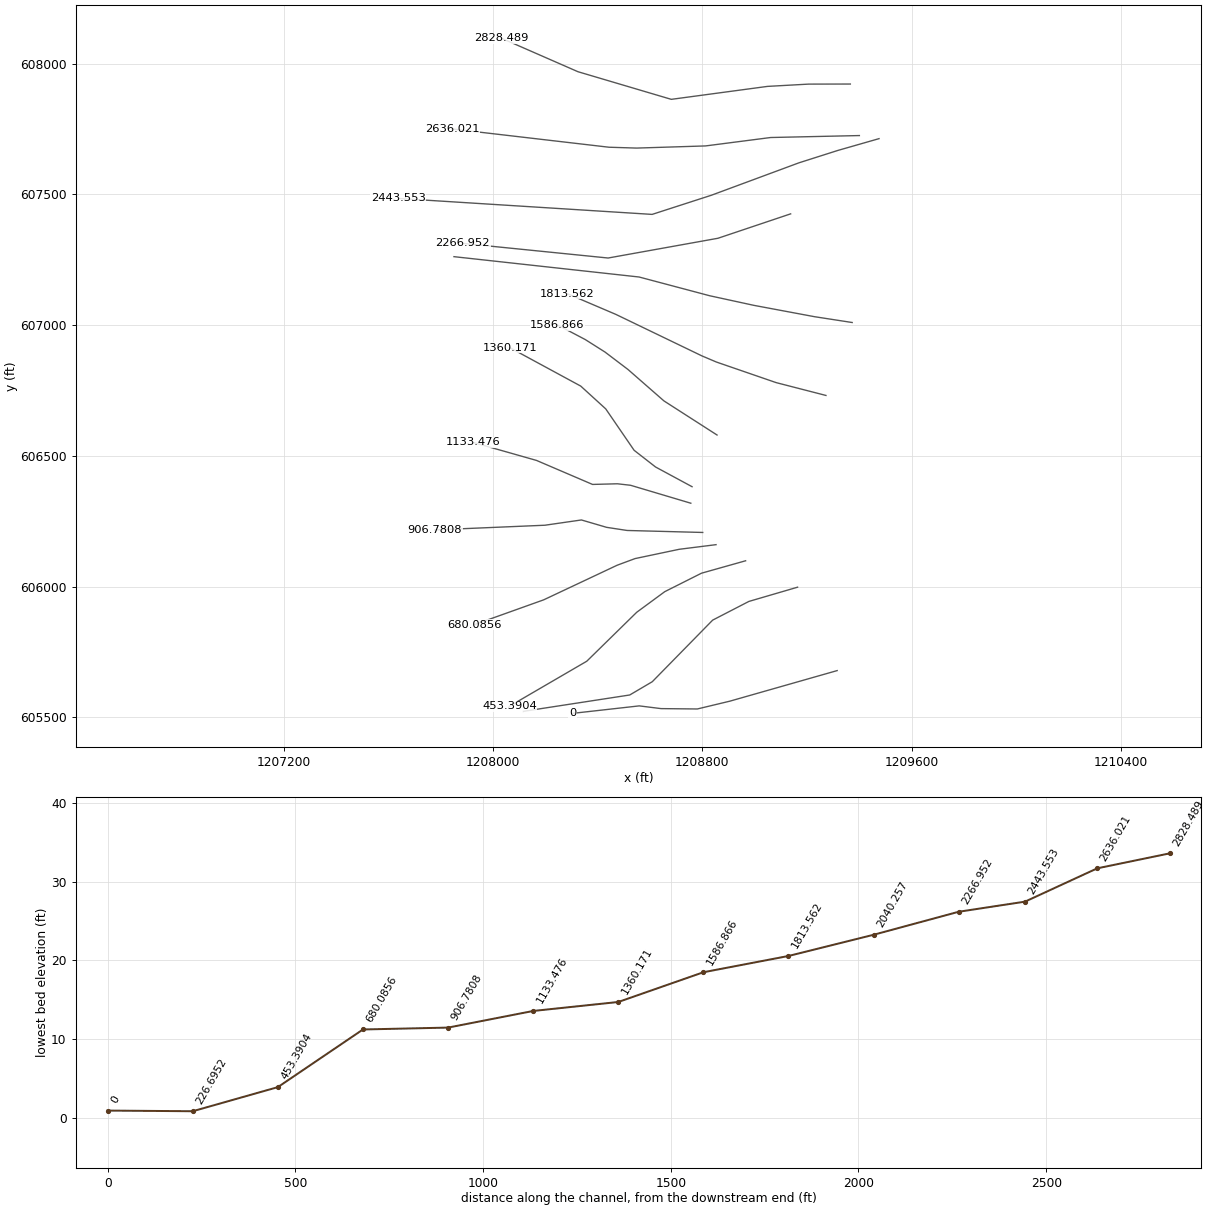
HEC-RAS study 60_ras.prj: 60

--- 60_ras.g01 (geometry) --- (continued)

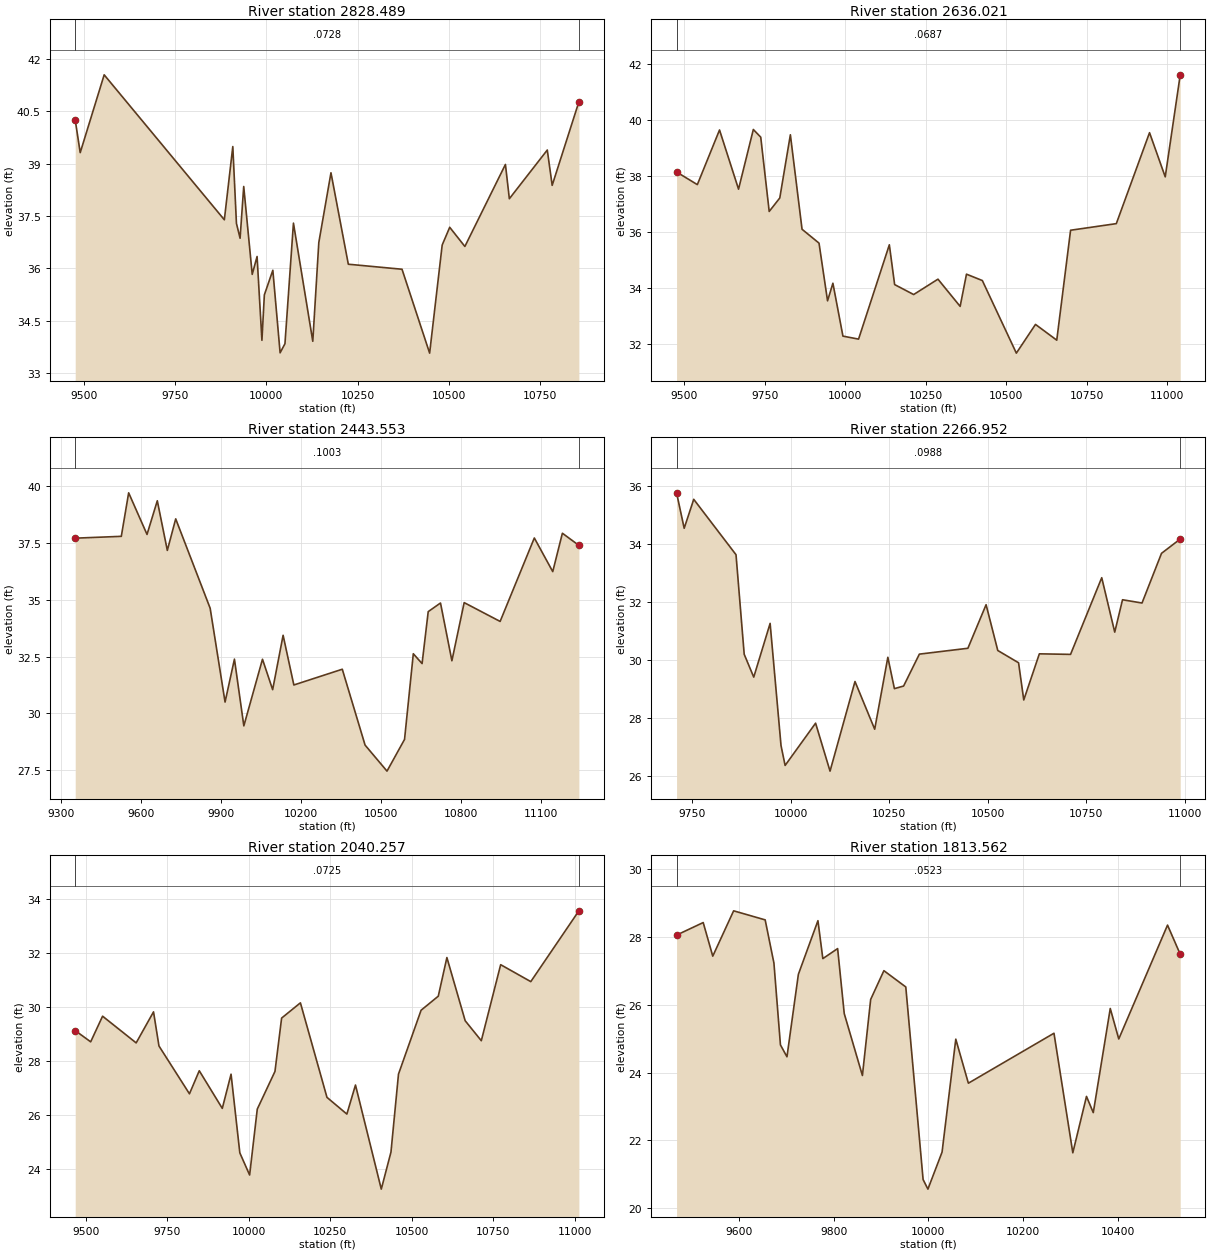
Type RM Length L Ch R = 1 ,2828.489,192.467700,192.467700,192.467700
XS GIS Cut Line= 6
 1209365.8336952607921.5945094231209206.43555909607921.303077444
1209048.97246262 607912.560184361208681.33832771607863.053773955
1208324.42263469 607968.700494261208032.75596803608096.304660916
#Sta/Elev= 30
9477.04940.251659490.70939.315179556.32641.546179885.29637.390499908.44739.48982
9918.41137.287039928.37636.86102 9938.3438.344959961.59135.825469974.877 36.3386
9988.16333.935759994.80635.2375910018.0435.9436710037.9533.5772510051.2333.83823
10074.4637.2951810127.4133.9077910143.8936.7377710177.1938.7383210224.6836.11675
10371.6835.9727510447.2933.5681810481.6536.6671610502.2737.1755310543.7636.62564
10654.7838.9768310665.5237.9941810769.3739.3907810782.7838.3774710855.8940.77211
#Mann= 3 , 0 , 0
9477.049  0.0728       09477.049  0.0728       010855.89  0.0728       0
#XS Ineff= 2 , 0
       0                10184.03       0
Bank Sta=9477.049,10855.89
Exp/Cntr=0.3,0.1

Type RM Length L Ch R = 1 ,2636.021,192.467700,192.467700,192.467700
XS GIS Cut Line= 6
1209400.31716847607724.6215615121209061.16779751607717.133957803
1208812.28225762 607684.982157321208549.06542146 607676.75568226
1208443.10945603607680.0037506221207842.65180135 607749.95049426
#Sta/Elev= 30
9475.86738.149149540.41537.698289609.31339.65102 9668.3837.535429714.33139.66894
9737.31439.393059763.59836.739069796.45337.220229829.35139.479529865.59936.10242
9918.32535.607269944.83233.544669961.44734.173839992.60332.2837110041.1632.17678
10136.7535.5477710153.19 34.125510212.2933.7698110287.75 34.319110356.6633.34668
10376.36 34.498110425.5934.2698310531.23  31.67610590.6832.7022310656.7432.13894
10699.6836.0677410841.7136.3038110944.89 39.554510993.6537.9750611040.2341.62202
#Mann= 3 , 0 , 0
9475.867  0.0687       09475.867  0.0687       011040.23  0.0687       0
#XS Ineff= 2 , 0
       0                10201.06       0
Bank Sta=9475.867,11040.23
Exp/Cntr=0.3,0.1

Type RM Length L Ch R = 1 ,2443.553,176.601200,176.601200,176.601200
XS GIS Cut Line= 6
1209475.52774218607712.8231822251209318.69756284 607667.92543681
1209169.28290263607620.3783056441208834.62828004607496.462749898
1208607.94958711607423.2030363381207636.92263466 607484.32549426
#Sta/Elev= 30
9352.45737.721549525.21637.802329552.75939.720589621.618 37.88669660.147 39.3714
 9697.71 37.18229729.12638.572569858.28434.631619914.14930.496699949.30532.38904
9984.53129.4459310054.4232.3840310092.5631.0432210131.71 33.441210172.0131.24955
10353.5331.94367   1043928.5994710521.18 27.451810586.9328.85002 10619.832.62693
10652.68 32.192310675.6934.4829610721.7134.8632410764.4532.3173110810.4734.88056
10945.2534.0507411073.4537.7300111142.4936.2473911178.6537.9390811240.4837.40373
#Mann= 3 , 0 , 0
9352.457  0.1003       09352.457  0.1003       011240.48  0.1003       0
#XS Ineff= 2 , 0
       0                10256.65       0
Bank Sta=9352.457,11240.48
Exp/Cntr=0.3,0.1

Type RM Length L Ch R = 1 ,2266.952,226.695200,226.695200,226.695200
XS GIS Cut Line= 4
1209137.57367632607425.2977164831208859.79589856 607331.98174426
1208439.71210328607256.440360025  1207884.318468607312.450494274
#Sta/Elev= 30
9710.00735.760789729.35434.538829753.58135.536749860.87233.627759881.63830.19637
9905.865 29.40949947.397 31.26149975.08527.050639985.46926.3660410062.7927.82253
10099.4526.1701310162.79 29.258510212.7927.6140510246.1330.0931210262.79 29.0128
10286.1329.1023510326.1330.2019210449.2630.4038710495.4231.90526 10525.130.32748
10577.8629.9038210591.0528.6222410630.6230.2122710709.7630.1934410788.8932.83603
10821.8730.9604710841.6532.0760610891.1231.9633910940.5833.6755110988.0734.16826
#Mann= 3 , 0 , 0
9710.007  0.0988       09710.007  0.0988       010988.07  0.0988       0
#XS Ineff= 2 , 0
       0                10370.75       0
Bank Sta=9710.007,10988.07
Exp/Cntr=0.3,0.1

Type RM Length L Ch R = 1 ,2040.257,226.695200,226.695200,226.695200
XS GIS Cut Line= 6
1209372.80709547 607009.880192191209228.74722314607032.129457191
1208996.92978793607075.4925415521208828.01038471607112.205161989
1208558.25280911607183.8287499991207850.46160883607261.596037716
#Sta/Elev= 30
9467.29629.129159514.73228.712399551.24929.662979654.30828.672849707.61329.82343
9724.27128.558979817.88126.785379847.98427.639879918.61326.245329945.52127.51241
9972.42924.5968610002.5123.7753910025.9926.21835 10080.327.6148410100.6629.59224
10158.3730.1576210239.8426.6539610300.9426.0336910327.3427.1106310406.5623.25191
10436.2624.6244510459.3727.5161610528.6829.8830110581.4930.4049910607.8931.83621
   1066429.4943810713.5128.7539110772.9231.5720110865.3430.9441911012.9533.56869
#Mann= 3 , 0 , 0
9467.296  0.0725       09467.296  0.0725       011012.95  0.0725       0
#XS Ineff= 2 , 0
       09908.643        10443.16       0
Bank Sta=9467.296,11012.95
Exp/Cntr=0.3,0.1

Type RM Length L Ch R = 1 ,1813.562,226.695200,226.695200,226.695200
XS GIS Cut Line= 6
1209272.52746529606731.0329320211209082.14438068606780.092633447
1208853.80955944 606858.74576549 1208798.5695419 606882.16127003
1208469.68133731607040.7708820331208283.98497244607120.012430192
#Sta/Elev= 30
9467.33728.062949523.69628.433399543.916 27.44179588.05128.779739654.75628.51266
 9673.2727.237519687.06324.821769700.855   24.479724.99226.905559766.36928.48853
9776.71427.368549808.02227.66471    982225.74601 9860.44 23.91829877.91226.16367
9905.87527.013149952.19926.531819988.80820.84765    999920.56362 10028.921.65595
10057.9524.9908610084.5623.6908710265.6325.1657710305.4721.6365510334.4123.30035
10348.7822.82201 10384.725.8960110402.6624.9965410505.8228.3578810532.6827.49745
#Mann= 3 , 0 , 0
9467.337  0.0523       09467.337  0.0523       010532.68  0.0523       0
#XS Ineff= 2 , 0
       09763.469                       0
Bank Sta=9467.337,10532.68
Exp/Cntr=0.3,0.1

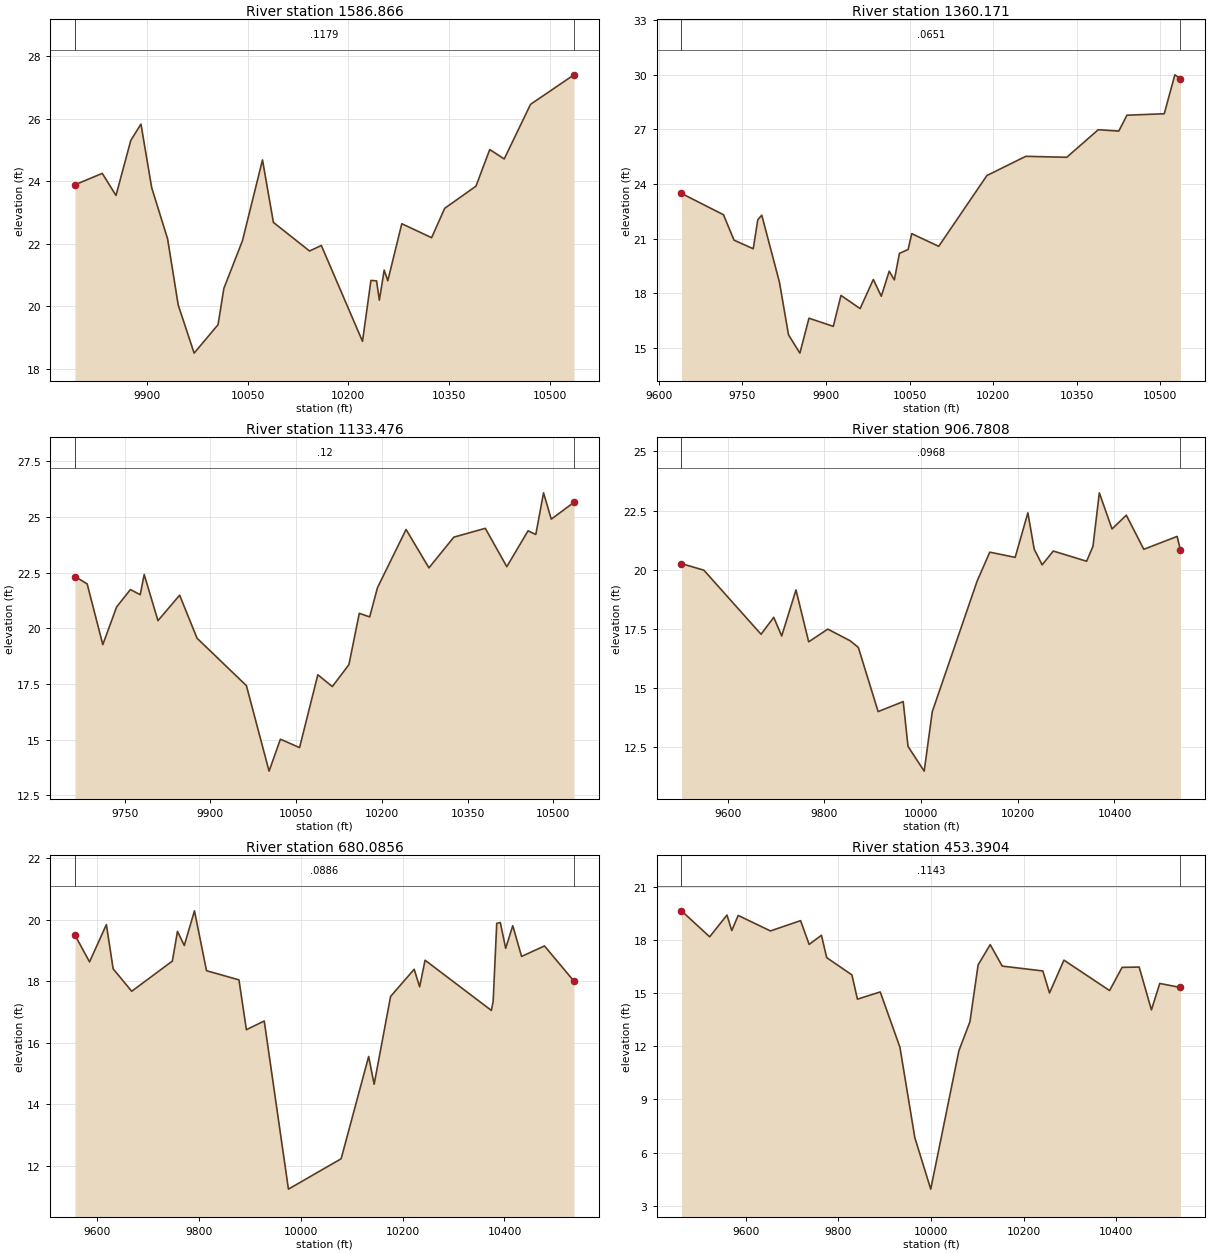
Type RM Length L Ch R = 1 ,1586.866,226.695200,226.695200,226.695200
XS GIS Cut Line= 6
1208856.18347651606579.7713829431208653.04776633606710.252985805
1208515.82049564606830.2280606781208427.79767308606896.995255873
1208352.19349957606944.8029261981208246.27850205607000.497290954
#Sta/Elev= 30
9792.89523.888879833.52924.253479853.98823.54757 9876.0625.308099891.19225.83047
9907.17923.796399930.89722.156889946.70920.041999970.42718.5006410006.0719.41159
 10014.720.5695610042.4422.09882 10072.324.6834810088.5422.6845510142.3821.76938
10159.97 21.945510221.3118.8779810233.8720.8275410242.2420.8125510246.4320.19619
10253.6121.1574110258.9920.8167710279.8622.6419210324.2822.19546 10343.823.13537
10390.3823.8436910410.9125.0157910432.4924.71516 10471.726.4630110536.4527.40703
#Mann= 3 , 0 , 0
9792.895  0.1179       09792.895  0.1179       010536.45  0.1179       0
#XS Ineff= 2 , 0
       0                               0
Bank Sta=9792.895,10536.45
Exp/Cntr=0.3,0.1

Type RM Length L Ch R = 1 ,1360.171,226.695200,226.695200,226.695200
XS GIS Cut Line= 6
1208760.71751735606382.1400991231208621.17526442 606457.47029154
1208539.07374313606521.4239566331208430.68796936606679.613532215
1208335.13924769606766.7578437781208063.42389953606913.992559195
#Sta/Elev= 30
9640.65423.485429716.04322.318119735.05420.922579769.51220.452239777.68322.04106
9784.827 22.29189816.50818.622289832.82515.732719853.222 14.72969869.53916.64347
9913.19116.197619926.998 17.89329961.34117.173019985.06218.768569999.35817.84807
10013.5619.2201510022.8118.7434910031.9320.1993510047.5120.4097610053.9721.27976
10102.4420.5850210188.9224.4658410258.6825.5196410332.2425.4672210388.7626.97713
10425.65  26.90310440.3127.7735810507.2427.8530910526.2829.9877410536.3529.77789
#Mann= 3 , 0 , 0
9640.654  0.0651       09640.654  0.0651       010536.35  0.0651       0
#XS Ineff= 2 , 0
       09693.397                       0
Bank Sta=9640.654,10536.35
Exp/Cntr=0.3,0.1

Type RM Length L Ch R = 1 ,1133.476,226.695200,226.695200,226.695200
XS GIS Cut Line= 6
1208755.91935018606319.0223563611208525.64400965606387.594876856
1208475.04235831606393.3383063521208380.22364184606390.836394906
1208166.00680682606482.6054871831207922.55581224606551.729905143
#Sta/Elev= 30
9663.104 22.32269684.41121.992099711.79819.266049735.93120.957439760.06421.73576
9777.30221.506769784.19722.412389808.32920.342139846.231 21.48419876.66919.55514
 9963.1417.4243510002.7713.5913810022.5815.0228610056.1314.6475810088.0517.91429
10113.4617.38493 10142.518.3690310160.6520.6717810178.8120.5092210192.4621.82206
10242.5124.4322610282.5122.7097310326.0624.0872510381.15 24.483810418.7722.76326
   1045624.3733210469.5424.2074310483.07 26.076310496.61 24.895310536.3725.64978
#Mann= 3 , 0 , 0
9663.104    0.12       09663.104    0.12       010536.37    0.12       0
#XS Ineff= 2 , 0
       09781.236                       0
Bank Sta=9663.104,10536.37
Exp/Cntr=0.3,0.1

Type RM Length L Ch R = 1 ,906.7808,226.695200,226.695200,226.695200
XS GIS Cut Line= 6
1208801.52542546606207.2172585431208512.34772468 606214.84213464
1208434.14480561606226.7799763831208337.62478486606255.030566618
 1208198.1004906606234.8740122171207777.06473723606217.011100322
#Sta/Elev= 30
 9504.5320.255759550.99519.97569 9669.1117.269419695.38717.984739711.81117.19618
9741.37619.142379767.65516.948529807.15317.487129853.59516.990899870.29816.71309
9911.26114.000169963.11614.422469973.074  12.52710006.4911.4829510023.2313.99665
10115.8319.50907 10142.1  20.73910194.6420.5194310220.9122.4026110234.04 20.8626
10250.4620.2027310273.4520.7869410342.4120.3554810355.5420.9879410368.6823.24768
10394.9521.71985 10424.522.3029610460.6220.8597110529.5821.4049210536.4620.82173
#Mann= 3 , 0 , 0
 9504.53  0.0968       0 9504.53  0.0968       010536.46  0.0968       0
#XS Ineff= 2 , 0
       09732.497                       0
Bank Sta=9504.53,10536.46
Exp/Cntr=0.3,0.1

Type RM Length L Ch R = 1 ,680.0856,226.695200,226.695200,226.695200
XS GIS Cut Line= 6
1208852.38415912606160.5851933811208711.67914501606142.904920623
1208542.78356442606107.3640970891208474.16226155606081.900028497
1208193.62640196605949.7129300091207929.06085408605855.090242222
#Sta/Elev= 30
9557.32919.501689585.88718.632329618.93919.843229632.18718.407089668.61917.67657
9748.426 18.65849758.42619.624939771.76119.164399791.76220.29136 9815.39 18.3453
9879.061 18.04729893.65116.427869928.68516.70998 9976.1411.2453110079.5612.23197
10133.53 15.556210144.3314.6543110176.56 17.506910222.8918.3919310233.5817.82256
10244.2718.6860810374.3317.0533710377.8417.3434910384.8619.8833810391.8919.91102
10402.4219.0726810416.3219.80807 10433.618.8089110478.5219.1499510536.4618.00452
#Mann= 3 , 0 , 0
9557.329  0.0886       09557.329  0.0886       010536.46  0.0886       0
#XS Ineff= 2 , 0
       09836.017                       0
Bank Sta=9557.329,10536.46
Exp/Cntr=0.3,0.1

Type RM Length L Ch R = 1 ,453.3904,226.695200,226.695200,226.695200
XS GIS Cut Line= 6
1208965.43561961606098.9836453941208796.74301231606051.491703953
1208656.24579908605980.8451909971208549.15123692605902.139159895
1208358.14467665605714.9420199841208062.11517851605542.576118378
#Sta/Elev= 30
9461.33319.649949522.22818.183899559.62819.410929569.95318.535989583.80719.38959
9653.46118.514769718.47819.095259737.06517.753079763.54318.26994 9774.8917.00757
9829.40916.030759841.28414.662349890.53215.068889932.97311.951519965.2666.833218
9999.5673.93467510060.3711.7519610084.1513.3838410101.8416.5965410127.9717.74263
10153.8516.5289310241.5716.25458   1025615.0123710287.1216.8647310385.6915.14763
10412.6716.4572410449.5316.4739610476.0514.0570310494.05 15.548810538.7215.32249
#Mann= 3 , 0 , 0
9461.333  0.1143       09461.333  0.1143       010538.72  0.1143       0
#XS Ineff= 2 , 0
       0                               0
Bank Sta=9461.333,10538.72
Exp/Cntr=0.3,0.1

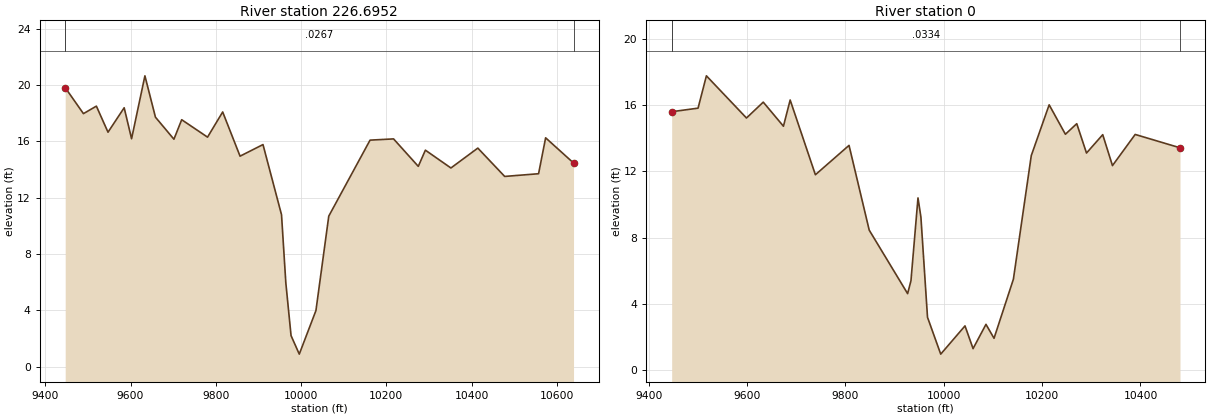
Type RM Length L Ch R = 1 ,226.6952,226.695200,226.695200,226.695200
XS GIS Cut Line= 6
1209164.12493521605998.0268300031208977.77751487605943.503963813
1208839.46366155605872.1096232531208608.58134931605636.598948732
1208522.33930135 605585.887994261208116.08930132 605523.38799426
#Sta/Elev= 30
9446.68719.801739489.46517.955449519.82318.488939547.11316.63756 9585.0218.37343
9602.40216.173099633.68920.640879658.40717.70383 9701.7616.139799719.98517.52397
9780.62316.286879816.15118.073939856.90914.935459910.70615.759269954.18810.77978
9964.3045.9391869976.5632.1927419995.8550.87858910034.963.97377310065.0510.67845
 10161.916.0739410217.0516.1623610275.0814.2122910291.7315.3617710351.61 14.0965
10414.7415.5082610477.7813.4962810557.2813.6892310573.8416.2389710639.2914.45177
#Mann= 3 , 0 , 0
9446.687  0.0267       09446.687  0.0267       010639.29  0.0267       0
#XS Ineff= 2 , 0
       0                               0
Bank Sta=9446.687,10639.29
Exp/Cntr=0.3,0.1

Type RM Length L Ch R = 1 ,       0,0.000000,0.000000,0.000000
XS GIS Cut Line= 6
 1209315.4347893605679.1442236451208904.89418533605562.184257641
 1208780.7717931605532.4157368241208642.13096803605533.804660916
1208558.79763469605544.2213275881208303.58930129 605515.57549426
#Sta/Elev= 30
9446.43315.612839500.10615.828589517.08917.782519598.60815.232989632.72716.19201
9673.78114.736769687.46616.320629738.78311.802799807.20713.578619848.2618.456033
9926.4064.6166429933.1795.3994969947.46910.402949953.3969.2504719966.8423.188508
9993.7330.96104510043.122.66784610059.521.29405210085.772.76116110102.171.917827
10141.565.49010110177.9312.96182 10214.316.0300110247.3314.2509510270.4414.88952
10290.2513.1155210323.2614.2252710343.0712.3559310389.2914.2389810480.4413.43289
#Mann= 3 , 0 , 0
9446.433  0.0334       09446.433  0.0334       010480.44  0.0334       0
#XS Ineff= 2 , 0
       0                               0
Bank Sta=9446.433,10480.44
Exp/Cntr=0.3,0.1